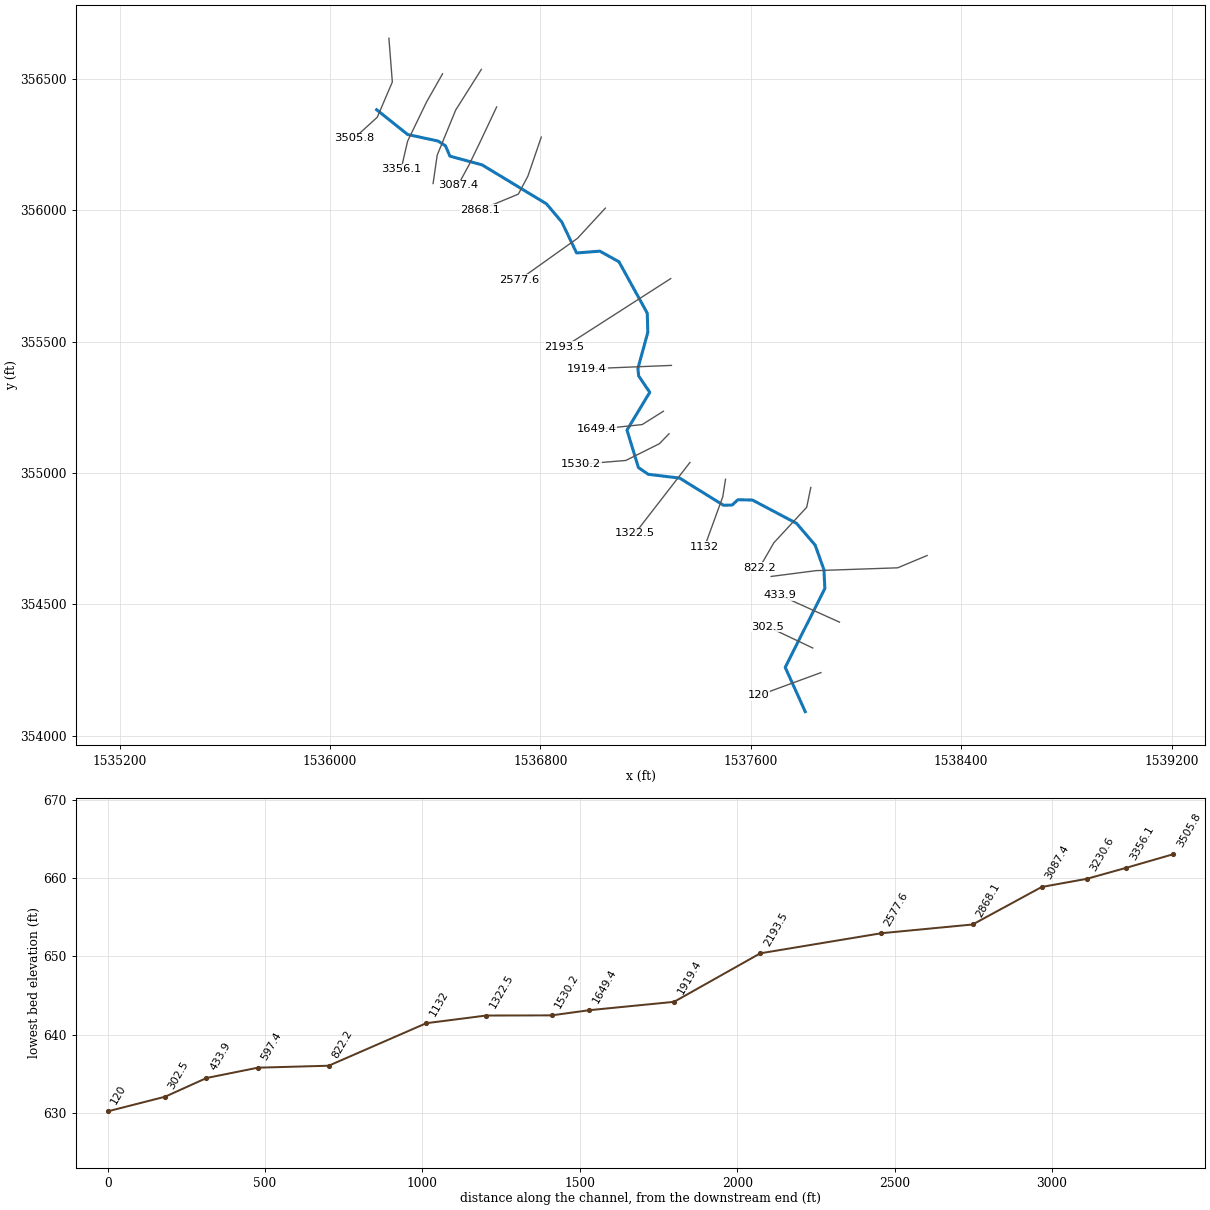
--- SHEETSRN.prj (project) ---

Proj Title=SHEETSRN
Current Plan=p01
Default Exp/Contr=0,0
English Units
Geom File=g01
Flow File=f01
Plan File=p01
BEGIN DESCRIPTION:
END DESCRIPTION:
DSS Export Rating Curves= 0
DSS Export Rating Curve Sorted= 0
DSS Export Volume Flow Curves= 0
DXF OffsetX= 0
DXF OffsetY= 0
DXF ScaleX= 0
DXF ScaleY= 0

--- SHEETSRN.p01 (plan) ---

Plan Title=Floodplain
Program Version=4.00
Geom File=g01
Flow File=f01
K Sum by GR=0
Std Step Tol=0.01
Critical Tol=0.01
Num of Std Step Trials=20
Max Error Tol=0.3
Flow Tol Ratio=0.001
Split Flow NTrial=30
Split Flow Tol=0.02
Split Flow Ratio=0.02
Log Output Level=0
Friction Slope Method=1
Unsteady Friction Slope Method=2
Unsteady Bridges Friction Slope Method=1
Global Log Level=0
CheckData=False
Run HTab=0
Run UNet=0
Run PostProcess=0
UNET Theta=0
UNET Theta Warmup=0
UNET ZTol=0
UNET ZSATol=0
UNET MxIter=0
UNET MaxInSteps=0
UNET DtIC=0
UNET DtMin=0
UNET MaxCRTS=0
UNET WFStab=0
UNET SFStab=0
UNET WFX=0
UNET SFX=0
UNET DSS MLevel=0
UNET DZMax Abort=0
UNET Convert EG Bridges=0
UNET Use Existing IB Tables=0
UNET Froude Limit=0
UNET Froude Power=0
Write IC File=0
Echo Input=False
Echo Output=False
Write Detailed=0

--- SHEETSRN.f01 (steady flow) ---

Flow Title=NFF Regression Equation
Program Version=4.10
Number of Profiles= 1
Profile Names=P100yr
River Rch & RM=SHEETSRN,Main            ,3505.8
900.4564
River Rch & RM=SHEETSRN,Main            ,597.4
 981.044
Boundary for River Rch & Prof#=SHEETSRN,Main            , 1
Up Type= 0
Dn Type= 3
Dn Slope=0.01
DSS Import GetInterval= 0
DSS Import GetPeak= 0
DSS Import FillOption= 0

--- SHEETSRN.g01 (geometry) ---

Geom Title=USGS 10m DEM
Program Version=4.10

River Reach=SHEETSRN        ,Main
Reach XY= 30
     1536177.325      356383.574     1536295.598      356289.173
     1536411.034      356264.317     1536439.121      356246.358
     1536456.188      356206.707     1536578.699      356173.446
     1536823.252       356025.06     1536881.412      355956.049
     1536937.835      355837.993     1537025.943      355844.938
      1537098.86      355804.573      1537206.47      355608.798
      1537208.64      355535.881      1537170.88       355397.86
     1537173.918      355369.648     1537216.018      355307.149
      1537129.37      355163.427     1537173.015      355020.534
     1537210.255      354995.013     1537329.786       354980.43
     1537496.452      354877.044     1537529.265      354877.826
      1537551.14      354898.138     1537606.609      354896.836
     1537774.143      354808.069     1537844.977      354725.083
      1537878.31       354631.68     1537881.782      354560.152
     1537731.088      354259.457     1537807.226       354090.81

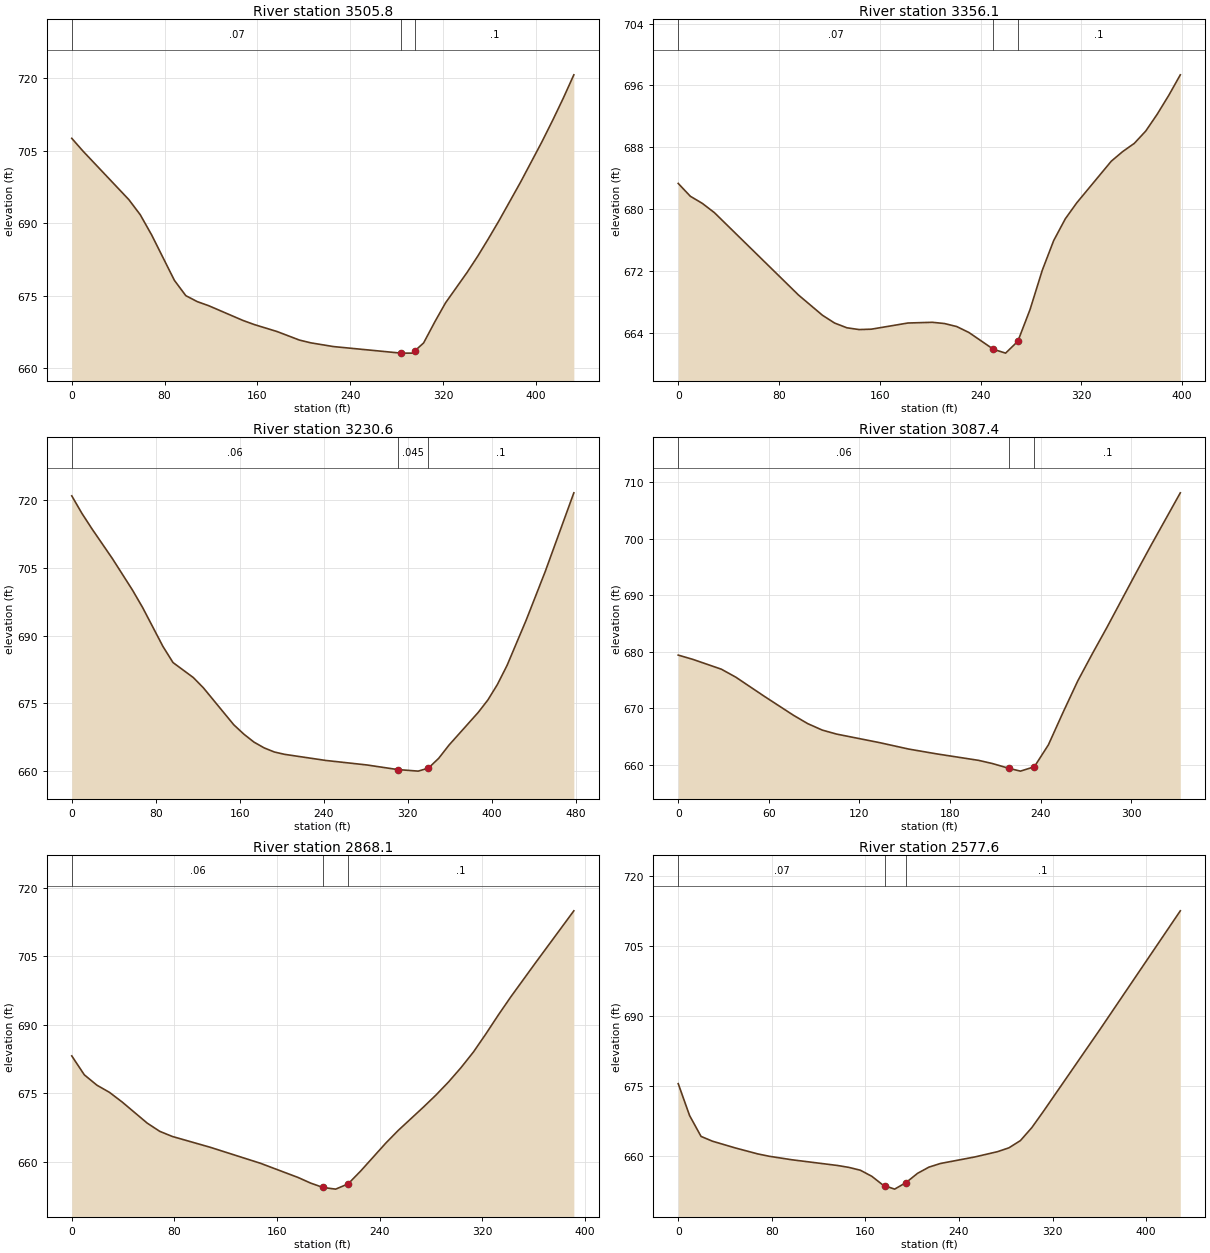
Type RM Length L Ch R = 1 ,3505.8  ,150.4,149.7,148.6
XS GIS Cut Line= 4
     1536224.183      356655.825     1536237.204      356489.158
     1536179.912      356355.044      1536091.37      356274.315
#Sta/Elev= 30
       0  707.58     9.8   704.9    49.2  694.88      59  691.76    68.8  687.59
    88.5  678.14    98.3  674.98   108.2  673.74     118   672.9   147.5  669.85
   157.3  668.99   176.9  667.55   196.3  665.77   206.1   665.2   225.5  664.43
   283.8  663.07   293.6  663.07   295.8  663.55   303.3  665.18     313  669.57
   322.2  673.49   340.7  679.77   349.9  683.14   359.1  686.76   368.3  690.52
   386.8  698.47   405.2  706.82   414.4  711.24   423.6  715.85   432.8  720.74
#Mann= 3 , 0 , 0
       0     .07       0   283.8    .045       0   295.8      .1       0
Bank Sta=283.8,295.8
XS Rating Curve= 0 ,0
Exp/Cntr=0.3,0.1

Type RM Length L Ch R = 1 ,3356.1  ,123.9,125.5,126.9
XS GIS Cut Line= 4
     1536428.077      356520.322     1536366.879      356412.249
     1536295.265      356263.811     1536270.525       356157.04
#Sta/Elev= 30
       0   683.3     9.6  681.64    19.1  680.72    28.7  679.52    95.5  668.85
   114.6  666.22   124.2  665.22   133.9  664.61   143.6  664.38   153.3  664.43
   182.4  665.23   201.8  665.32   211.4  665.16   221.1  664.77   230.8     664
   250.2  661.83   259.9  661.33   269.6  662.86   279.3  666.97     289  672.05
   298.1  675.91   307.3  678.72   316.4  680.79   343.8  686.18   352.9  687.43
   362.1  688.49   371.2  690.09   380.3  692.27   389.5  694.72   398.6  697.36
#Mann= 3 , 0 , 0
       0     .07       0   250.2    .045       0   269.6      .1       0
Bank Sta=250.2,269.6
XS Rating Curve= 0 ,0
Exp/Cntr=0.3,0.1

Type RM Length L Ch R = 1 ,3230.6  ,143.8,143.2,141.5
XS GIS Cut Line= 4
     1536575.745      356537.335     1536478.089      356382.387
     1536407.776      356210.512     1536392.151       356102.44
#Sta/Elev= 30
       0  720.98     9.6  717.12    19.3  713.64    38.6  707.09    57.8  700.08
    67.5  696.19    86.8  687.58    96.4     684   115.7  680.68   125.3   678.4
   154.2  670.21   163.9  668.11   173.5  666.35   183.2  665.07   192.9  664.16
   202.7  663.64   241.8  662.29   280.9  661.29   310.2  660.27   329.8  659.92
   339.5  660.59   349.3  662.75   359.1  665.68   387.1  672.98   396.2  675.72
   405.2  679.13   414.4  683.36   432.6   693.4   450.8  704.22     478  721.65
#Mann= 3 , 0 , 0
       0     .06       0   310.2    .045       0   339.5      .1       0
Bank Sta=310.2,339.5
XS Rating Curve= 0 ,0
Exp/Cntr=0.3,0.1

Type RM Length L Ch R = 1 ,3087.4  ,220,219.4,218.8
XS GIS Cut Line= 4
     1536633.807      356394.019     1536568.702      356255.999
     1536528.338      356172.665     1536486.671      356095.842
#Sta/Elev= 25
       0  679.43     9.5  678.69    28.6  676.93    38.2  675.51    57.2   672.1
    76.3  668.78    85.8  667.29    95.4  666.15   104.9  665.44   133.5  663.92
   152.6  662.79   171.1  661.94   198.9  660.79   208.2  660.22   219.1  659.37
   226.7  658.88   235.9  659.65   245.2  663.53   254.9  669.27   264.6  674.82
   274.3  679.66     284  684.34   303.5   694.1   313.2  698.87   332.6  708.17
#Mann= 3 , 0 , 0
       0     .06       0   219.1    .045       0   235.9      .1       0
Bank Sta=219.1,235.9
XS Rating Curve= 0 ,0
Exp/Cntr=0.3,0.1

Type RM Length L Ch R = 1 ,2868.1  ,300.9,290.4,279.9
XS GIS Cut Line= 4
      1536803.61      356279.523     1536752.829      356131.085
      1536716.37      356062.075     1536571.839      356002.179
#Sta/Elev= 28
       0  683.21     9.8  679.07    19.6  676.81    29.4  675.24    39.2  673.15
    58.8  668.52    68.6  666.72    78.4   665.6   107.9  663.24   147.1  659.74
   176.4  656.64   186.2  655.41   195.9  654.45   205.7  654.09   215.4  655.23
   225.2  658.04   244.7  664.12   254.5  666.92     274  671.98   283.8  674.62
   293.6  677.48   303.4  680.63   313.2  684.09   322.9  688.05   332.7  692.22
   342.5  696.21     362  703.74   391.4  714.92
#Mann= 3 , 0 , 0
       0     .06       0   195.9    .045       0   215.4      .1       0
Bank Sta=195.9,215.4
XS Rating Curve= 0 ,0
Exp/Cntr=0.3,0.1

Type RM Length L Ch R = 1 ,2577.6  ,382.5,384.1,383.2
XS GIS Cut Line= 3
     1537047.099       356008.69     1536941.631      355894.106
     1536718.974      355735.252
#Sta/Elev= 27
       0  675.51     9.7   668.7    19.5  664.24    29.2  663.22    48.7  661.78
    68.1  660.49    77.9  659.99    97.3  659.24   136.3  658.02     146  657.61
   155.7  657.01   165.5  655.71   175.3  653.79   176.4   653.7     185  652.97
   194.8  654.38   204.6  656.35   214.3  657.67   224.1  658.45   253.4  659.84
     273  660.98   282.7   661.8   292.5  663.34   302.3  666.13     312  669.53
   360.9  687.24   429.2  712.46
#Mann= 3 , 0 , 0
       0     .07       0   176.4    .045       0   194.8      .1       0
Bank Sta=176.4,194.8
XS Rating Curve= 0 ,0
Exp/Cntr=0.3,0.1

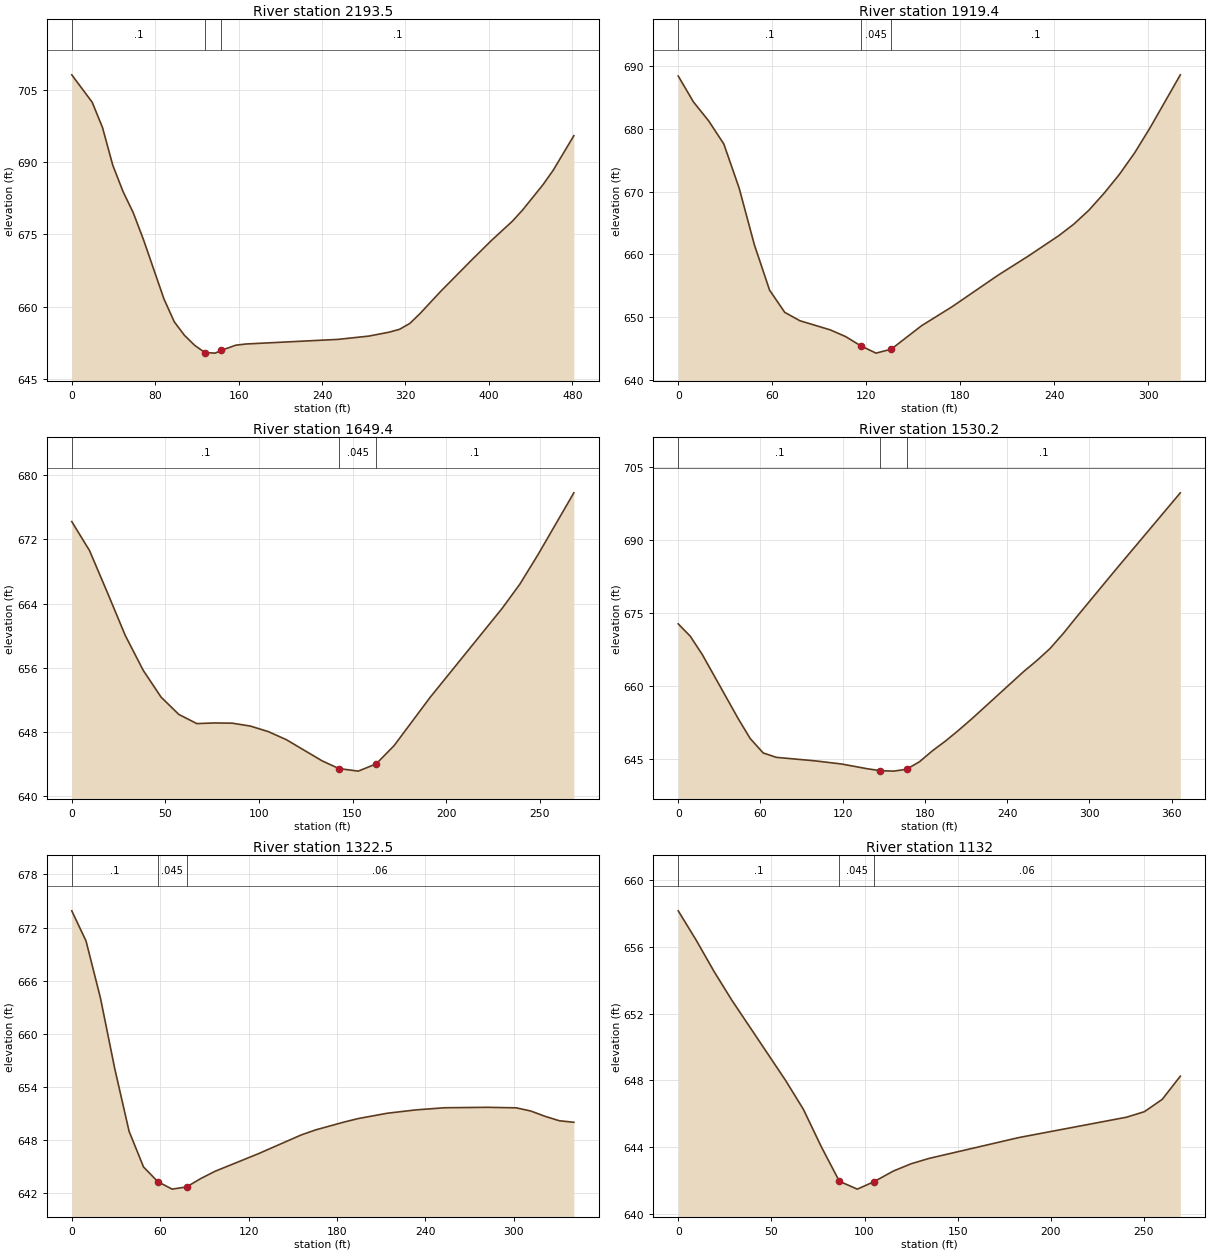
Type RM Length L Ch R = 1 ,2193.5  ,285.8,274.1,261.9
XS GIS Cut Line= 2
     1537295.797       355740.46     1536890.849      355480.044
#Sta/Elev= 30
       0  708.05    19.6  702.37    29.5  697.12    39.3  689.35    49.1  683.91
      59  679.47    68.8   673.9    88.4  661.64    98.3   656.9   108.1  654.09
   117.9  652.02   127.7  650.53   137.6  650.41   143.4  650.98   157.2  652.05
     167   652.3   255.5  653.26   284.9  653.94   304.6  654.76   314.4  655.35
   324.2  656.56   334.1  658.63   353.7  663.18   383.2  669.63   402.8  673.81
   422.5  677.72   432.3  680.04     452  685.32   461.8  688.32   481.5  695.44
#Mann= 3 , 0 , 0
       0      .1       0   127.7    .045       0   143.4      .1       0
Bank Sta=127.7,143.4
XS Rating Curve= 0 ,0
Exp/Cntr=0.3,0.1

Type RM Length L Ch R = 1 ,1919.4  ,266.5,270,270.6
XS GIS Cut Line= 2
     1537298.401      355409.731     1536978.089       355396.71
#Sta/Elev= 26
       0  688.44     9.7  684.31    19.4  681.29    29.1   677.6    38.9  670.55
    48.6  661.52    58.3  654.28      68  650.72    77.7  649.38    97.1  647.92
   106.9  646.85   116.6  645.37   126.3  644.21     136  644.84   155.4  648.59
   174.9  651.62     204  656.61   223.4  659.68   242.9  662.94   252.6   664.8
   262.3  667.04     272  669.75   281.7  672.74   291.4  676.16   301.2  680.14
   320.6  688.63
#Mann= 3 , 0 , 0
       0      .1       0   116.6    .045       0     136      .1       0
Bank Sta=116.6,136
XS Rating Curve= 0 ,0
Exp/Cntr=0.3,0.1

Type RM Length L Ch R = 1 ,1649.4  ,112.3,119.2,127.5
XS GIS Cut Line= 3
     1537267.921      355235.165     1537187.192      355184.384
     1537015.317      355166.155
#Sta/Elev= 23
       0  674.22     9.5   670.6    19.1  665.34    28.6  660.03    38.2  655.68
    47.7  652.36    57.2   650.2    66.8  649.06    76.3  649.14    85.8  649.11
    95.4  648.75     105  648.06   114.6  647.06   133.8  644.41   142.7  643.46
     153  643.14   162.6  644.04   172.2  646.32   191.4  652.32   229.8  663.38
   239.4  666.44     249  670.08   268.2   677.8
#Mann= 3 , 0 , 0
       0      .1       0   142.7    .045       0   162.6      .1       0
Bank Sta=142.7,162.6
XS Rating Curve= 0 ,0
Exp/Cntr=0.3,0.1

Type RM Length L Ch R = 1 ,1530.2  ,196,207.6,216.6
XS GIS Cut Line= 4
     1537289.287      355149.315     1537252.829      355111.554
     1537125.224      355047.752     1536954.651      355033.429
#Sta/Elev= 25
       0  672.79     8.8  670.24    17.5   666.5    43.7  653.31    52.5  649.19
      62  646.22    71.5  645.32     100  644.59   119.1  643.95   138.1  642.96
   147.5  642.57   157.1  642.48   166.6  642.86   176.1  644.43   185.6   646.7
   195.2  648.72   204.7  650.93   214.2  653.25   252.2  663.02   261.7  665.25
   271.2   667.7   280.7  670.74   290.2  674.06   318.8  683.82   366.3  699.76
#Mann= 3 , 0 , 0
       0      .1       0   147.5    .045       0   166.6      .1       0
Bank Sta=147.5,166.6
XS Rating Curve= 0 ,0
Exp/Cntr=0.3,0.1

Type RM Length L Ch R = 1 ,1322.5  ,183,190.5,197.7
XS GIS Cut Line= 2
     1537368.714       355039.94     1537160.381      354770.408
#Sta/Elev= 25
       0  673.89     9.7  670.48    19.5  664.02    29.2  656.04    38.9  648.99
    48.7  644.96    58.4   643.3    68.1  642.46    77.9  642.71    87.6  643.66
    97.3  644.48   126.5  646.45   155.7  648.58   165.5  649.15   184.9  650.04
   194.7  650.44   214.1  651.03   233.6  651.41   253.1  651.65   282.3   651.7
   301.7  651.64   311.5  651.28   321.2  650.68   330.9  650.18   340.7  650.01
#Mann= 3 , 0 , 0
       0      .1       0    58.4    .045       0    77.9     .06       0
Bank Sta=58.4,77.9
XS Rating Curve= 0 ,0
Exp/Cntr=0.3,0.1

Type RM Length L Ch R = 1 ,1132    ,318.1,309.9,300.3
XS GIS Cut Line= 3
     1537504.131      354976.137     1537493.714      354909.731
     1537424.704      354719.627
#Sta/Elev= 18
       0  658.16     9.6  656.41    19.2  654.53    28.8   652.8    57.6     648
    67.2  646.26    76.8  644.02    86.5  641.95    96.1  641.48     105  641.92
   115.4  642.56     125     643   134.6  643.32   182.8  644.57   240.6  645.79
   250.2  646.12   259.8  646.86   269.5  648.25
#Mann= 3 , 0 , 0
       0      .1       0    86.5    .045       0     105     .06       0
Bank Sta=86.5,105
XS Rating Curve= 0 ,0
Exp/Cntr=0.3,0.1

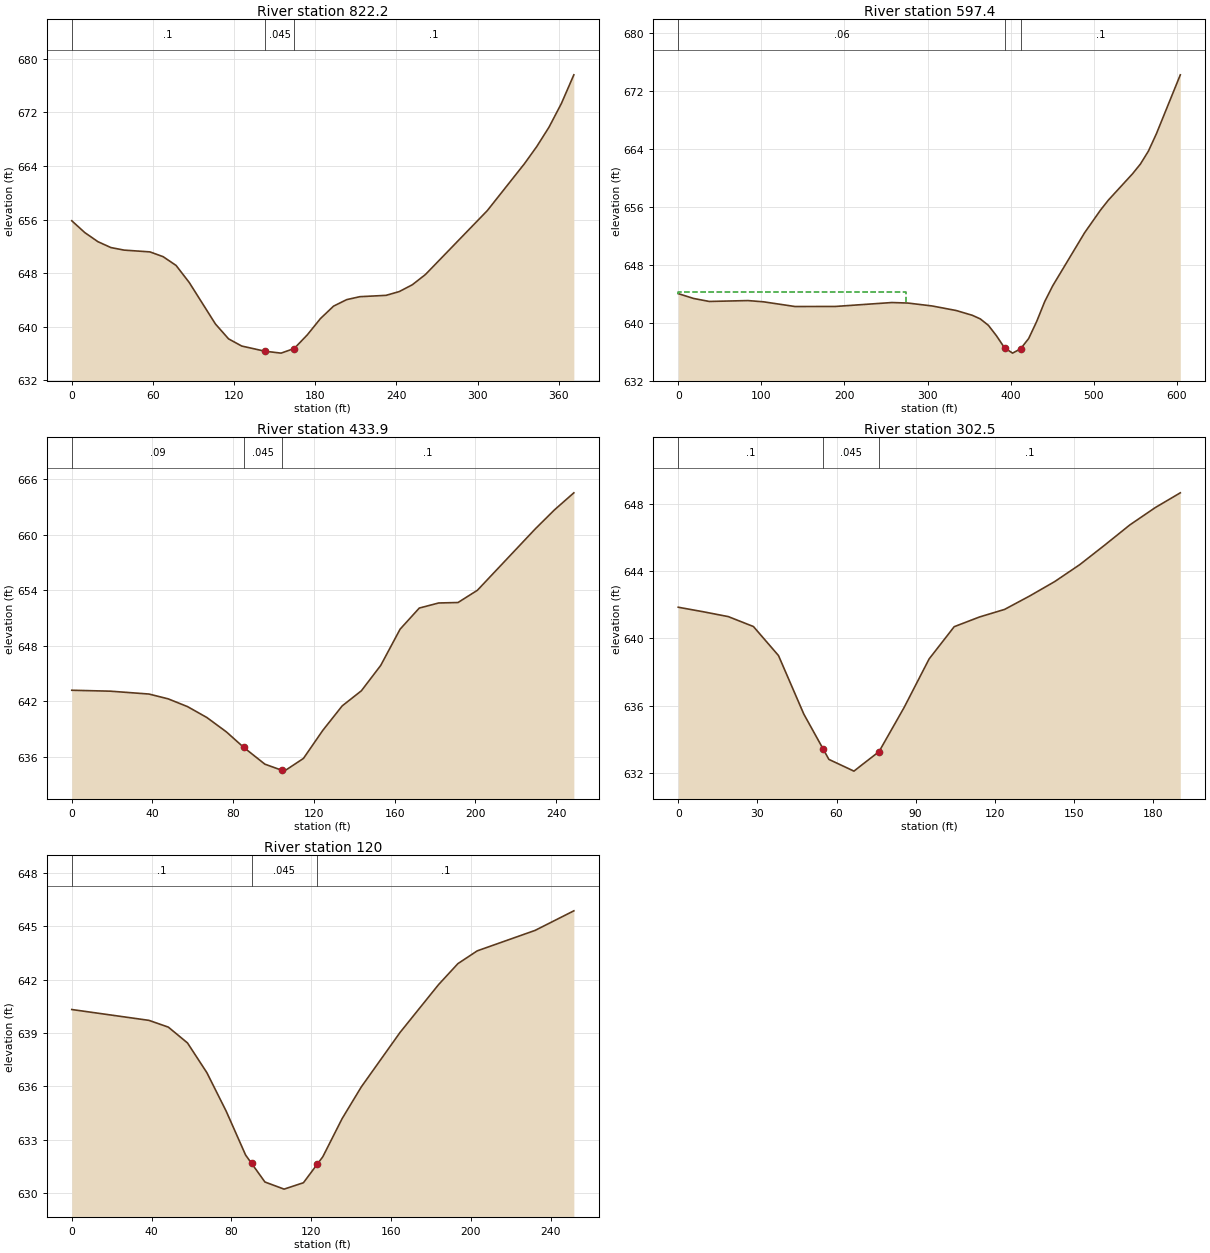
Type RM Length L Ch R = 1 ,822.2   ,242.3,224.8,206.5
XS GIS Cut Line= 4
     1537828.349      354944.887     1537812.724      354869.367
     1537687.724       354733.95     1537633.037      354638.898
#Sta/Elev= 30
       0  655.82     9.6  654.06    19.3   652.7    28.9  651.82    38.6  651.44
    57.8  651.17    67.5  650.46    77.1  649.15    86.8  646.61   106.2   640.4
   115.9  638.18   125.6  637.11   142.6  636.34   154.7  636.05   164.4  636.74
   174.1  638.78   183.8  641.21   193.5  643.07   203.2  644.04   212.9  644.48
   232.3  644.68     242  645.24   251.7  646.26   261.4  647.79   307.1  657.33
   334.5  664.32   343.7  666.91   352.8  669.82   361.9  673.34   371.1  677.62
#Mann= 3 , 0 , 0
       0      .1       0   142.6    .045       0   164.4      .1       0
Bank Sta=142.6,164.4
XS Rating Curve= 0 ,0
Exp/Cntr=0.3,0.1

Type RM Length L Ch R = 1 ,597.4   ,173.9,163.4,153.1
XS GIS Cut Line= 4
     1538270.558      354685.627     1538158.745      354638.765
     1537848.896      354628.058     1537677.586      354605.867
#Sta/Elev= 30
       0  644.01    18.6  643.34    37.3  642.93    83.9  643.05   102.6  642.88
   140.6  642.23   189.1  642.24   256.9  642.78   276.2  642.71   305.3  642.31
   334.4  641.68   353.8  641.02   363.4  640.52   373.1  639.64   382.8   638.2
   392.5  636.54   402.2   635.8   411.9   636.4   421.6  637.82   431.3  640.19
   440.9  642.92   450.5  645.09   488.8   652.4     508  655.54   517.6  656.93
   546.4  660.53     556  661.89   565.6  663.67   575.2  666.06     604   674.2
#Mann= 3 , 0 , 0
       0     .06       0   392.5    .045       0   411.9      .1       0
#XS Ineff= 2 , 0
          273.69  644.18
Permanent Ineff=
       F       F
Bank Sta=392.5,411.9
XS Rating Curve= 0 ,0
Exp/Cntr=0.3,0.1

Type RM Length L Ch R = 1 ,433.9   ,132.1,131.5,131.1
XS GIS Cut Line= 2
     1537937.343      354431.874     1537710.607      354534.304
#Sta/Elev= 24
       0  643.21    19.1  643.11    38.3   642.8    47.8  642.28    57.4  641.44
      67  640.26    76.6  638.72    85.2637.0452    95.7  635.23  104.07 634.576
   105.3  634.48   114.8  635.85   124.4  638.88     134  641.52   143.5  643.15
   153.1  645.89   162.7   649.8   172.2  652.08   181.8  652.63   191.4  652.68
     201     654   229.7  660.63   239.2  662.68   248.8  664.52
#Mann= 3 , 0 , 0
       0     .09       0    85.2    .045       0  104.07      .1       0
Bank Sta=85.2,104.07
XS Rating Curve= 0 ,0
Exp/Cntr=0.3,0.1

Type RM Length L Ch R = 1 ,302.5   ,163.9,182.5,199.6
XS GIS Cut Line= 2
     1537835.728      354333.342     1537663.853       354414.94
#Sta/Elev= 23
       0  641.86     9.5  641.59      19   641.3    28.5  640.71      38  638.98
    47.6  635.49      55  633.39    57.1  632.79    66.6  632.09      70  632.51
    76.1  633.25    85.6  635.88    95.1  638.78   104.6   640.7   114.2  641.28
   123.7  641.73   133.2  642.53   142.7  643.39   152.2   644.4   161.7  645.57
   171.2  646.77   180.8   647.8   190.3  648.68
#Mann= 3 , 0 , 0
       0      .1       0      55    .045       0    76.1      .1       0
Bank Sta=55,76.1
XS Rating Curve= 0 ,0
Exp/Cntr=0.3,0.1

Type RM Length L Ch R = 1 ,120     ,118.1,120,122
XS GIS Cut Line= 2
     1537866.978      354239.592     1537630.867      354152.787
#Sta/Elev= 21
       0  640.32    38.7  639.71    48.4  639.33      58  638.44    67.7  636.77
    77.4   634.6    87.1  632.14   90.08 631.673    96.8  630.62   106.4  630.22
   116.1  630.58  123.03631.6245   125.8  632.04   135.5  634.19   145.1  635.97
   164.5  639.03   183.8  641.72   193.5   642.9   203.2  643.62   232.2  644.77
   251.6  645.87
#Mann= 3 , 0 , 0
       0      .1       0   90.08    .045       0  123.03      .1       0
Bank Sta=90.08,123.03
XS Rating Curve= 0 ,0
Exp/Cntr=0.3,0.1

Chan Stop Cuts=-1
Use User Specified Reach Order=0
Composite Channel Slope=5

--- SHEETSRN.g02 (geometry) ---

Geom Title=USGS 10m DEM_old
Program Version=4.10

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
River Reach=SHEETSRN        ,Main

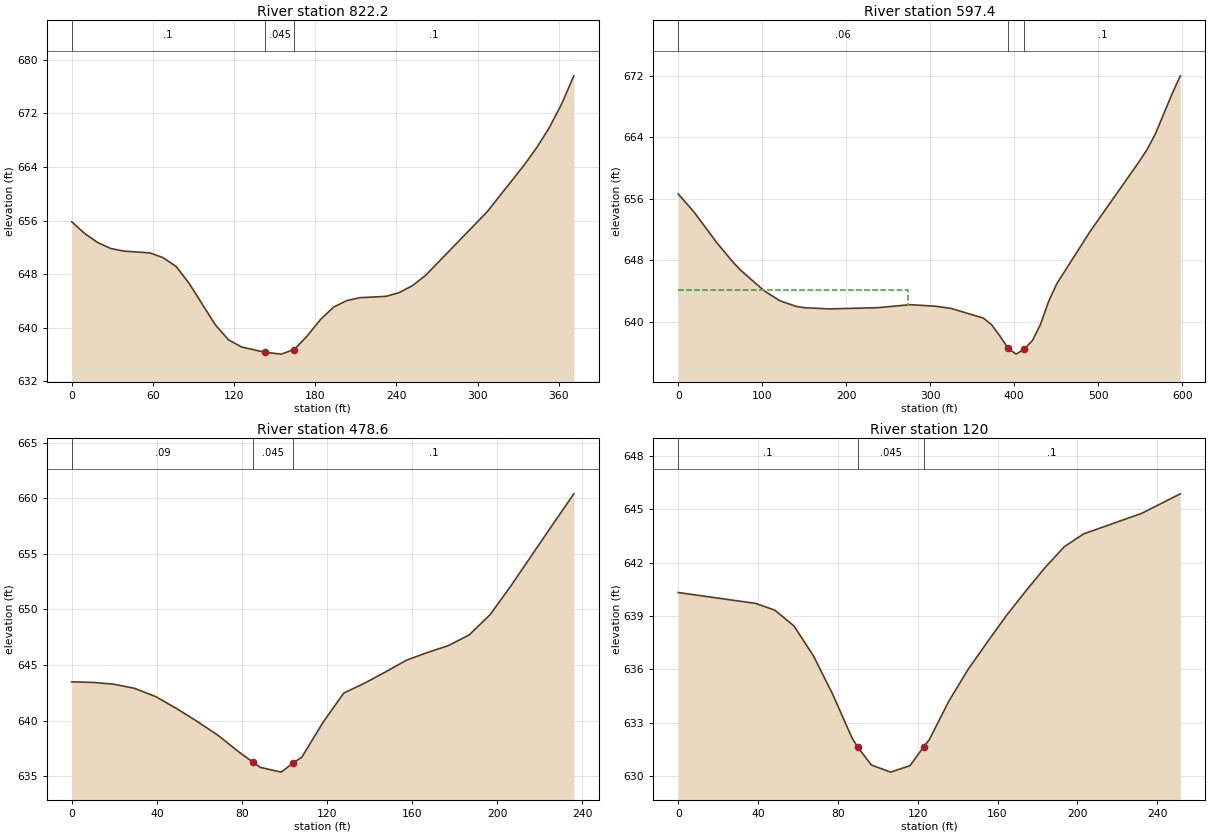
Type RM Length L Ch R = 1 ,822.2   ,234.1,224.8,215.4
XS GIS Cut Line= 4
     1537828.349      354944.887     1537812.724      354869.367
     1537687.724       354733.95     1537633.037      354638.898
#Sta/Elev= 30
       0  655.82     9.6  654.06    19.3   652.7    28.9  651.82    38.6  651.44
    57.8  651.17    67.5  650.46    77.1  649.15    86.8  646.61   106.2   640.4
   115.9  638.18   125.6  637.11   142.6  636.34   154.7  636.05   164.4  636.74
   174.1  638.78   183.8  641.21   193.5  643.07   203.2  644.04   212.9  644.48
   232.3  644.68     242  645.24   251.7  646.26   261.4  647.79   307.1  657.33
   334.5  664.32   343.7  666.91   352.8  669.82   361.9  673.34   371.1  677.62
#Mann= 3 , 0 , 0
       0      .1       0   142.6    .045       0   164.4      .1       0
Bank Sta=142.6,164.4
XS Rating Curve= 0 ,0
Exp/Cntr=0.3,0.1

Type RM Length L Ch R = 1 ,597.4   ,134.7,118.8,102.5
XS GIS Cut Line= 4
     1538222.447       354825.53     1538135.641      354740.894
     1537851.353      354617.197     1537688.592      354582.474
#Sta/Elev= 30
       0  656.62    18.6  654.31    46.6   650.2    65.3  647.75    74.6  646.68
   102.6  644.01   121.2  642.73   140.6     642   150.3  641.84   179.4  641.68
   237.5  641.84   276.2  642.23   305.3  642.04   324.7  641.75   363.4  640.48
   373.1  639.62   382.8  638.18   392.5  636.58   402.2   635.8   411.9  636.46
   421.6  637.57   431.3  639.68   441.1   642.7   450.8  644.98     490   651.7
   548.8  660.85   558.5  662.46   568.3  664.51   587.9  669.65   597.7  671.99
#Mann= 3 , 0 , 0
       0     .06       0   392.5    .045       0   411.9      .1       0
#XS Ineff= 2 , 0
          273.69  644.18
Permanent Ineff=
       F       F
Bank Sta=392.5,411.9
XS Rating Curve= 0 ,0
Exp/Cntr=0.3,0.1

Type RM Length L Ch R = 1 ,478.6   ,179.4,176.1,172.9
XS GIS Cut Line= 2
     1537953.783       354486.12     1537728.089      354555.565
#Sta/Elev= 28
       0  643.49     9.8  643.44    19.7  643.28    29.5  642.91    39.4  642.17
    49.2   641.1      59  639.93    68.9  638.66    78.7  637.17    85.2  636.27
    88.6   635.8    98.4  635.37   100.2  635.62  104.07  636.19   108.2  636.72
   118.1  639.83   127.9  642.48   137.8  643.38   147.6  644.39   157.4  645.44
   167.3  646.13   177.1  646.75   186.9  647.71   196.8  649.55   206.6  652.15
   216.5  654.93   226.3  657.68   236.1   660.4
#Mann= 3 , 0 , 0
       0     .09       0    85.2    .045       0  104.07      .1       0
Bank Sta=85.2,104.07
XS Rating Curve= 0 ,0
Exp/Cntr=0.3,0.1

Type RM Length L Ch R = 1 ,120     ,118.1,120,122
XS GIS Cut Line= 2
     1537866.978      354239.592     1537630.867      354152.787
#Sta/Elev= 23
       0  640.32    38.7  639.71    48.4  639.33      58  638.44    67.7  636.77
    77.4   634.6    87.1  632.14   90.08  631.61    96.8  630.62   106.4  630.22
   116.1  630.58  123.03  631.65   125.8  632.04   135.5  634.19   145.1  635.97
   154.8  637.52   164.5  639.03   174.2  640.41   183.8  641.72   193.5   642.9
   203.2  643.62   232.2  644.77   251.6  645.87
#Mann= 3 , 0 , 0
       0      .1       0   90.08    .045       0  123.03      .1       0
Bank Sta=90.08,123.03
XS Rating Curve= 0 ,0
Exp/Cntr=0.3,0.1